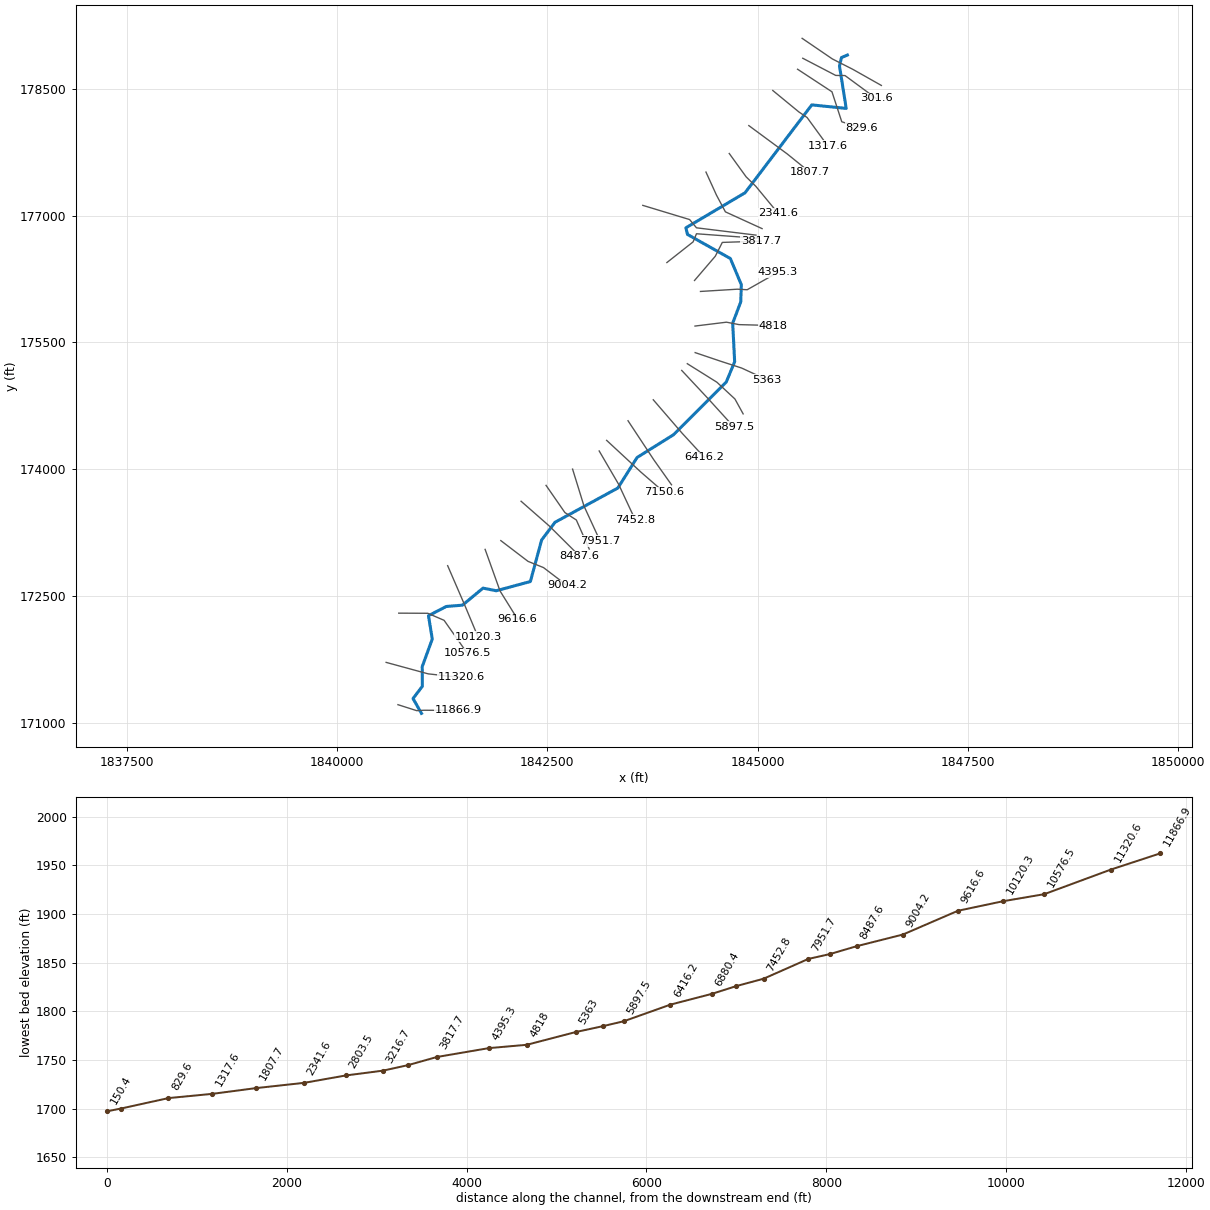
--- WhitOakBr2.prj (project) ---

Proj Title=WhitOakBr2
Current Plan=p01
Default Exp/Contr=0,0
English Units
Geom File=g01
Flow File=f01
Plan File=p01
BEGIN DESCRIPTION:
END DESCRIPTION:
DSS Export Rating Curves= 0
DSS Export Rating Curve Sorted= 0
DSS Export Volume Flow Curves= 0
DXF OffsetX= 0
DXF OffsetY= 0
DXF ScaleX= 0
DXF ScaleY= 0

--- WhitOakBr2.p01 (plan) ---

Plan Title=Floodplain
Program Version=4.00
Geom File=g01
Flow File=f01
K Sum by GR=0
Std Step Tol=0.01
Critical Tol=0.01
Num of Std Step Trials=20
Max Error Tol=0.3
Flow Tol Ratio=0.001
Split Flow NTrial=30
Split Flow Tol=0.02
Split Flow Ratio=0.02
Log Output Level=0
Friction Slope Method=1
Unsteady Friction Slope Method=2
Unsteady Bridges Friction Slope Method=1
Global Log Level=0
CheckData=False
Run HTab=0
Run UNet=0
Run PostProcess=0
UNET Theta=0
UNET Theta Warmup=0
UNET ZTol=0
UNET ZSATol=0
UNET MxIter=0
UNET MaxInSteps=0
UNET DtIC=0
UNET DtMin=0
UNET MaxCRTS=0
UNET WFStab=0
UNET SFStab=0
UNET WFX=0
UNET SFX=0
UNET DSS MLevel=0
UNET DZMax Abort=0
UNET Convert EG Bridges=0
UNET Use Existing IB Tables=0
UNET Froude Limit=0
UNET Froude Power=0
Write IC File=0
Echo Input=False
Echo Output=False
Write Detailed=0

--- WhitOakBr2.f01 (steady flow) ---

Flow Title=NFF Regression Equation
Program Version=4.00
Number of Profiles=1
Profile Names=P100yr
River Rch & RM=WhitOakBr2,Main      ,11866.9
280.1593
River Rch & RM=WhitOakBr2,Main      ,11866.9
346.8910
River Rch & RM=WhitOakBr2,Main      ,10120.3
365.5592
River Rch & RM=WhitOakBr2,Main      ,9616.6
489.1029
River Rch & RM=WhitOakBr2,Main      ,8191.2
518.4692
River Rch & RM=WhitOakBr2,Main      ,5662.3
574.3508
River Rch & RM=WhitOakBr2,Main      ,5363
911.7284
River Rch & RM=WhitOakBr2,Main      ,3496.5
943.1993
River Rch & RM=WhitOakBr2,Main      ,3216.7
1278.297
River Rch & RM=WhitOakBr2,Main      ,301.6
1328.135
Boundary for River Rch & Prof#=WhitOakBr2,Main      ,1
Up Type=0
Dn Type=3
Dn Slope=0.015414

--- WhitOakBr2.g01 (geometry) ---

Geom Title=USGS 10m DEM
Program Version=4.00

River Reach=WhitOakBr2      ,Main
Reach XY= 30
     1841004.877       171111.49     1840904.584      171286.667
      1841015.08      171432.261      1841013.78      171664.952
     1841133.376      171991.239     1841087.877      172266.829
     1841299.769      172376.024     1841492.162      172391.624
     1841736.552      172593.116     1841893.846      172561.917
     1842299.431      172671.113     1842432.541      173161.027
     1842591.919      173371.786      1843339.39       173777.37
     1843568.182      174138.756     1843999.765      174406.546
     1844627.641      175030.522     1844727.737      175271.013
     1844704.338      175727.295     1844800.344      175979.138
     1844807.034      176182.277     1844677.038      176491.665
     1844167.458      176776.355     1844147.855       176855.13
     1844851.149      177269.311     1845644.948      178309.362
     1846053.685      178267.397     1845973.952      178770.256
     1845997.885      178869.408     1846067.979      178898.915

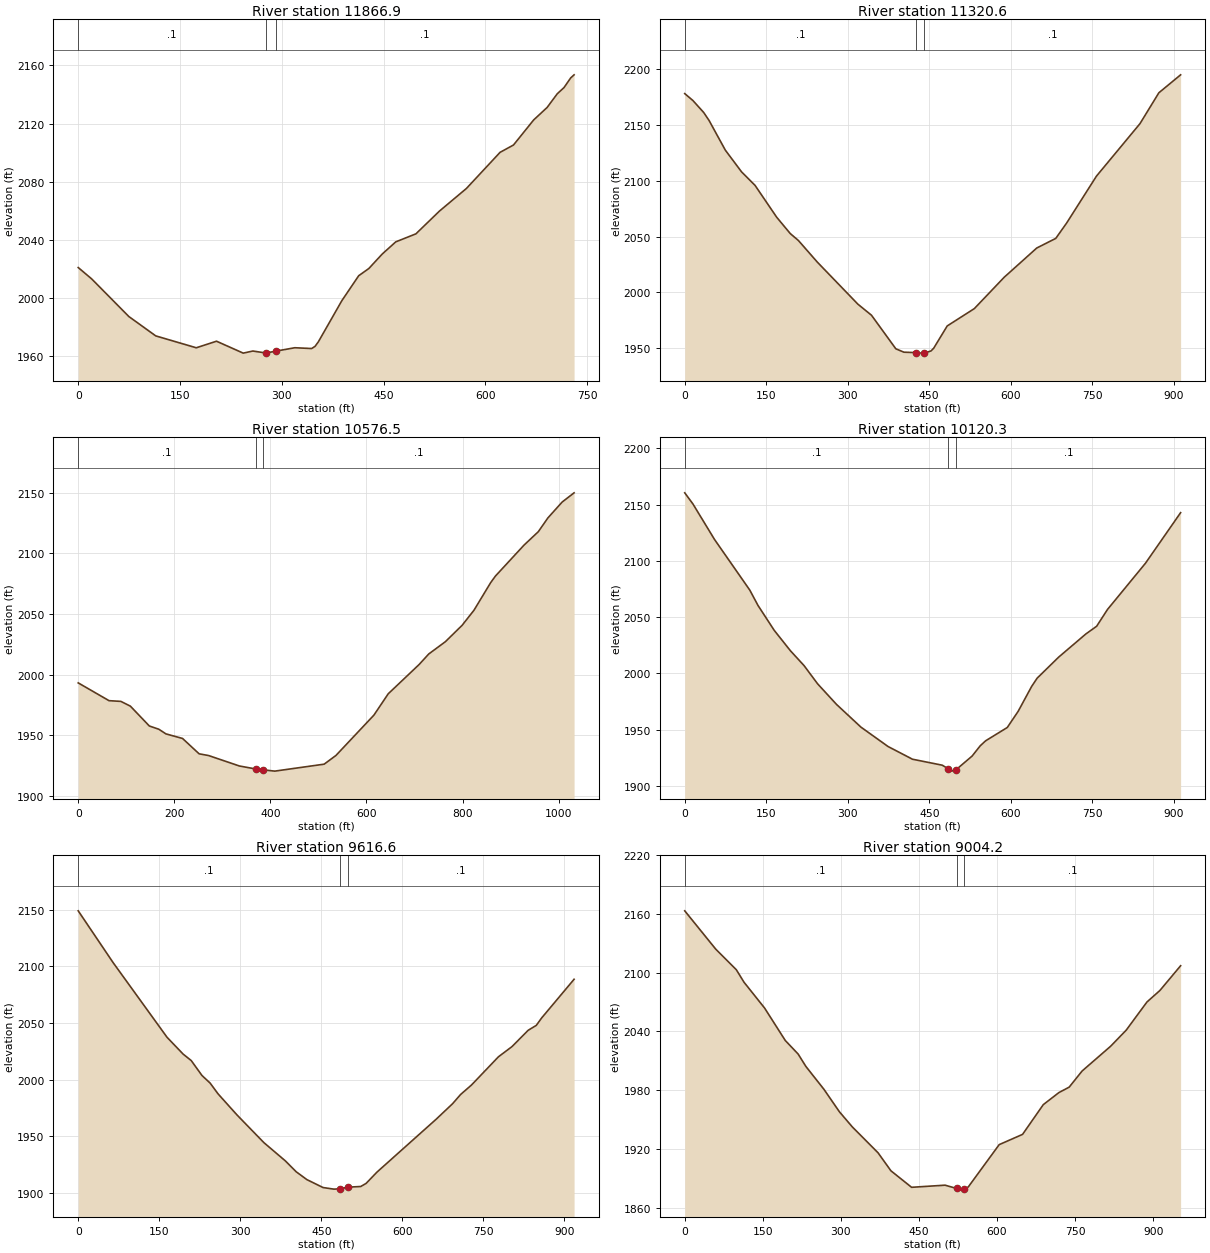
Type RM Length L Ch R = 1 ,11866.9 ,552.4,546.3,539.7
XS GIS Cut Line= 4
      1840725.13      171214.322     1840947.845      171143.709
     1841033.299       171148.42     1841444.816      171146.141
#Sta/Elev= 30
       0  2021.1    19.9 2013.26    74.6 1987.43   114.3  1974.1     174 1965.94
   203.8 1970.45   243.2 1962.26   257.4 1963.71   276.7 1962.34   291.7 1963.67
   319.2 1965.96     344 1965.42     349  1966.9   353.9 1970.01   388.6 1998.37
   413.4 2015.48   428.3 2020.42   448.1  2030.4     468 2038.75   497.7 2044.26
   532.4 2059.91   572.1 2075.44   621.7 2100.28   641.5 2105.33   671.2 2122.54
   691.1 2131.16     706 2140.54   715.9 2144.78   725.8 2151.45   730.8 2153.57
#Mann= 3 , 0 , 0
       0      .1       0   276.7    .045       0   291.7      .1       0
Bank Sta=276.7,291.7
XS Rating Curve= 0 ,0
Exp/Cntr=0.3,0.1

Type RM Length L Ch R = 1 ,11320.6 ,745.9,744.1,755.1
XS GIS Cut Line= 3
     1840584.743       171714.64     1841084.762      171578.864
     1841477.131      171536.071
#Sta/Elev= 30
       0 2177.99      15 2171.82    34.9  2161.1    44.8 2153.94    74.7 2127.41
   104.6 2107.96   129.5 2095.81   169.4 2067.26   194.3 2052.71   209.2 2046.55
   244.1 2027.16   318.8 1989.51   343.8 1979.62   388.6 1949.58   403.5 1946.56
   426.2 1946.17   438.4 1945.72   441.2 1945.79   453.4 1947.68   458.3 1950.13
   483.2 1970.07   533.1 1985.57   588.1 2013.64     648  2039.8     683 2048.41
     703 2062.16   757.9 2104.14   837.9 2151.04   872.8 2178.75   912.8  2194.8
#Mann= 3 , 0 , 0
       0      .1       0   426.2    .045       0   441.2      .1       0
Bank Sta=426.2,441.2
XS Rating Curve= 0 ,0
Exp/Cntr=0.3,0.1

Type RM Length L Ch R = 1 ,10576.5 ,475.7,456.2,423.8
XS GIS Cut Line= 4
     1840734.499      172296.984     1841079.964      172295.385
     1841273.489      172212.218     1841548.582      171823.569
#Sta/Elev= 30
       0 1993.17    64.2 1978.49    88.8 1977.91   108.6 1973.98   148.1  1957.6
   167.8 1954.94   182.6  1951.1   217.2 1947.33   251.7 1934.65   271.4 1933.24
   335.6 1924.61   370.1 1922.12   385.1 1921.46   409.2 1920.38     512 1926.12
   536.5 1933.28   615.6 1966.58   645.4 1984.17   709.9  2008.4   729.7 2016.99
   764.4 2027.16   799.2 2040.66   823.9  2053.1   858.7 2075.89   868.6 2081.29
   928.1 2106.81   957.9  2117.9   977.7  2129.2  1007.5 2142.34  1032.3 2149.93
#Mann= 3 , 0 , 0
       0      .1       0   370.1    .045       0   385.1      .1       0
Bank Sta=370.1,385.1
XS Rating Curve= 0 ,0
Exp/Cntr=0.3,0.1

Type RM Length L Ch R = 1 ,10120.3 ,505,503.7,502.5
XS GIS Cut Line= 3
     1841316.031       172858.52     1841514.995      172400.944
     1841675.501      172019.748
#Sta/Elev= 30
       0 2160.56      15 2150.73    54.9 2119.04   119.8 2074.04   134.7 2060.56
   164.7 2038.31   194.6 2020.12   219.5 2007.04   244.5 1990.81   279.4 1972.45
   324.3 1952.29   374.2 1935.05   419.1 1923.77     474 1918.44   484.8 1915.31
     494 1913.18   499.8 1914.62   528.9 1926.58   543.8  1935.7   553.8 1940.15
   593.6 1951.97   613.6 1966.32   638.5 1988.51   648.5 1995.78   688.3 2014.57
   738.2 2035.09   758.1 2041.98     778 2056.86   847.8 2097.91   912.6 2142.92
#Mann= 3 , 0 , 0
       0      .1       0   484.8    .045       0   499.8      .1       0
Bank Sta=484.8,499.8
XS Rating Curve= 0 ,0
Exp/Cntr=0.3,0.1

Type RM Length L Ch R = 1 ,9616.6  ,590.7,612.3,633.2
XS GIS Cut Line= 3
     1841761.435      173051.316      1841938.83      172559.282
     1842148.185      172224.395
#Sta/Elev= 30
       0 2148.97    64.8 2103.14   164.4  2037.4   194.3  2022.5   209.2 2016.85
   229.1 2003.66   244.1 1997.01     259 1987.38   293.9 1968.87   343.7 1944.41
   383.6 1928.24   403.5  1918.7   423.4 1911.74   453.3 1904.75   473.2 1903.36
   484.4  1903.6   499.4  1905.1     523 1905.67     533 1908.42     553 1918.34
     663  1965.2     693 1978.72     708 1986.92     728 1995.21     778 2020.17
     803 2029.13     833 2043.54     848 2047.87     858 2054.46     918 2088.57
#Mann= 3 , 0 , 0
       0      .1       0   484.4    .045       0   499.4      .1       0
Bank Sta=484.4,499.4
XS Rating Curve= 0 ,0
Exp/Cntr=0.3,0.1

Type RM Length L Ch R = 1 ,9004.2  ,529,516.6,503.2
XS GIS Cut Line= 4
     1841948.038      173155.153       1842271.5      172909.546
     1842455.428      172835.974     1842733.315      172625.496
#Sta/Elev= 30
       0 2163.18    59.4 2124.16    99.1 2103.05   113.9 2090.27   153.5 2063.84
   193.2 2030.74   217.9 2016.92   232.8 2004.24   267.5 1980.86   297.2 1957.94
   321.9 1942.54   371.5 1916.02   396.2 1897.66   435.9 1880.81   500.2 1882.98
   522.4 1879.63   534.9 1878.95   537.4 1879.17   544.8 1881.17   604.2 1924.39
   649.1 1934.86   688.9 1965.21   718.8 1977.51   738.7 1983.12   763.6 1999.63
   818.4 2024.91   848.3 2041.34   888.1 2070.06     913 2081.82   952.8 2107.09
#Mann= 3 , 0 , 0
       0      .1       0   522.4    .045       0   537.4      .1       0
Bank Sta=522.4,537.4
XS Rating Curve= 0 ,0
Exp/Cntr=0.3,0.1

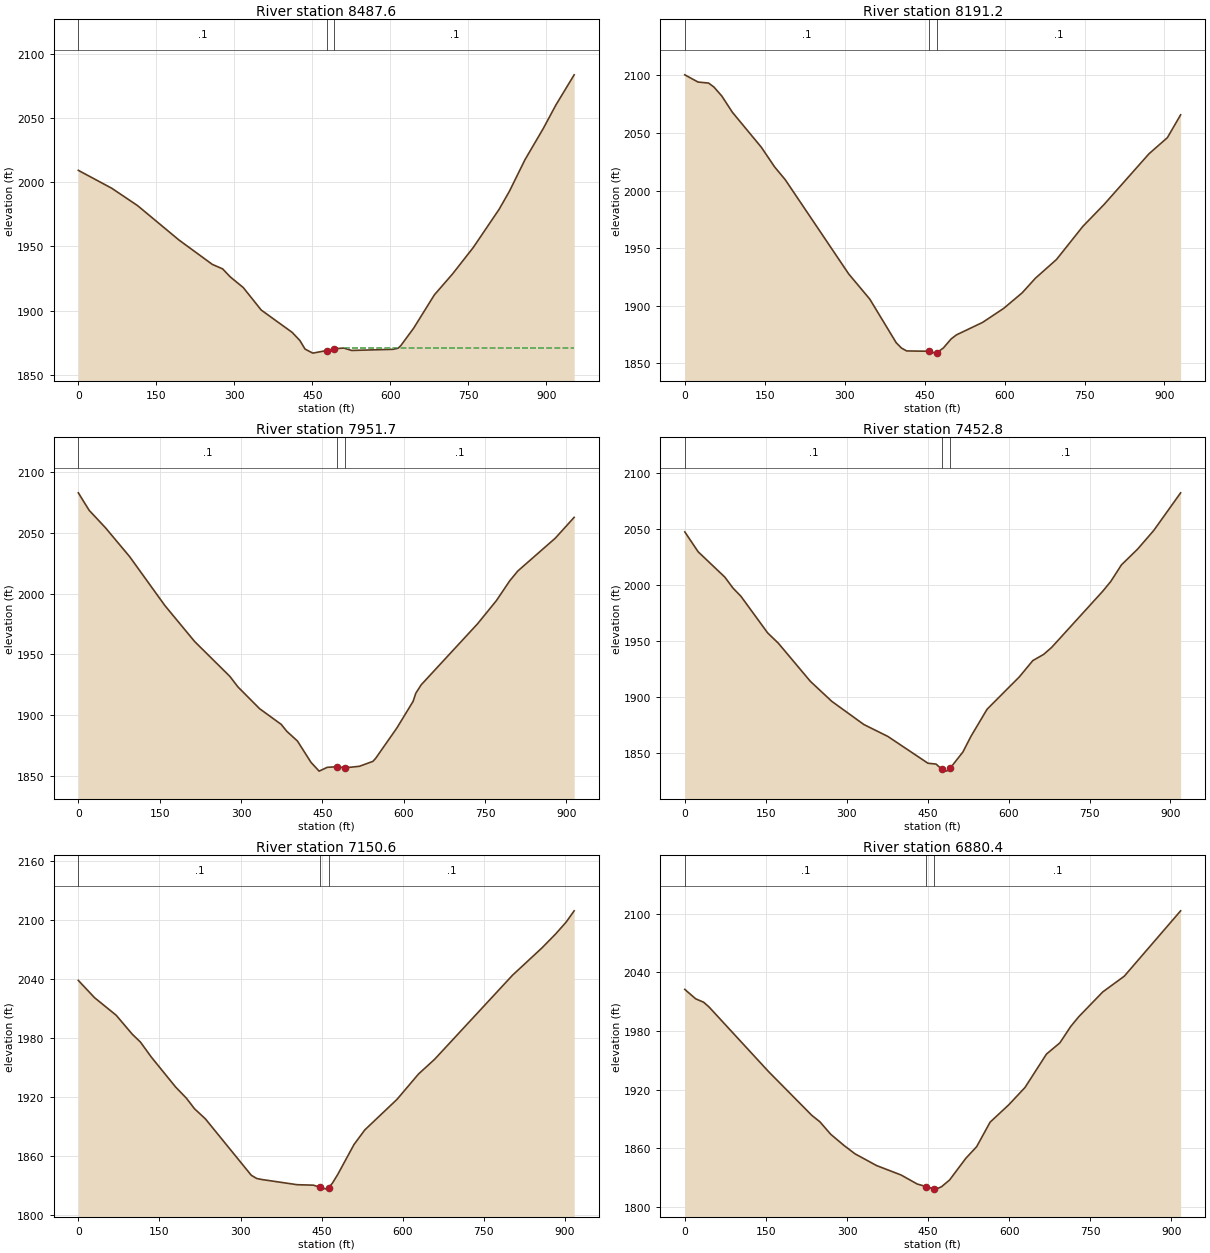
Type RM Length L Ch R = 1 ,8487.6  ,284,296.4,304.2
XS GIS Cut Line= 3
     1842188.992      173620.615     1842524.819      173327.502
     1842885.621      172970.738
#Sta/Elev= 30
       0 2009.26    64.4 1995.27   113.9 1981.79   193.2 1955.09   257.6 1936.01
   277.4 1932.54   292.2 1926.24     317 1918.02   351.6 1900.48   411.1 1883.08
   425.9 1876.77   435.8  1870.1   450.7 1866.93   477.3 1868.95   492.3 1870.35
   510.4 1870.89   525.4 1869.01   604.9  1869.9   614.9  1870.8   619.9 1872.75
   644.7  1886.4   684.5 1912.31   719.4 1928.58   759.2 1949.16   808.9 1978.89
   828.8 1993.01   858.6 2017.49   893.5  2041.6   918.3 2060.27   953.2 2083.62
#Mann= 3 , 0 , 0
       0      .1       0   477.3    .045       0   492.3      .1       0
#XS Ineff= 2 , 0
                          511.58         1870.92
Permanent Ineff=
       F       F
Bank Sta=477.3,492.3
XS Rating Curve= 0 ,0
Exp/Cntr=0.3,0.1

Type RM Length L Ch R = 1 ,8191.2  ,252.1,239.5,226.7
XS GIS Cut Line= 4
     1842485.816      173808.396     1842709.729      173486.921
     1842845.676      173398.955     1842999.216      173055.089
#Sta/Elev= 30
       0 2100.45    24.8 2094.19    44.6  2093.3    54.6 2089.89    69.4 2082.07
    89.3 2067.95   143.8 2037.48   168.6 2020.46   188.4 2009.46   307.5 1927.65
   347.1 1905.76   396.7 1867.89   406.5 1863.29   416.3 1860.79   458.4 1860.49
   470.3 1858.88   473.4 1859.42     485 1863.27   499.7 1871.19   509.5 1874.67
   558.6 1885.52   598.3  1897.7     633 1911.22   657.8 1923.88   697.4 1940.16
   746.9 1968.92   786.6 1987.87   870.8 2031.84   905.5 2045.94   930.3 2065.73
#Mann= 3 , 0 , 0
       0      .1       0   458.4    .045       0   473.4      .1       0
Bank Sta=458.4,473.4
XS Rating Curve= 0 ,0
Exp/Cntr=0.3,0.1

Type RM Length L Ch R = 1 ,7951.7  ,498.9,498.9,498.8
XS GIS Cut Line= 3
     1842801.057      174001.187     1842937.135      173562.849
     1843128.635      173149.791
#Sta/Elev= 30
       0 2083.15      20 2068.72    49.9 2054.46    94.8 2030.49   159.6 1990.31
   214.5 1960.66   279.4 1931.98   294.3 1923.31   334.2 1905.37   374.2 1892.39
   384.1 1886.88   404.1 1878.68     429 1861.18     444 1853.92     459 1857.05
   476.9 1857.55   491.9 1856.65   518.4 1857.91   543.1 1861.95     548 1864.29
   587.6 1889.61   617.3 1911.37   622.3 1918.06   632.2    1925   736.1 1975.24
   770.8 1994.31   795.5 2010.67   810.3 2018.72   879.6 2045.84   914.3 2062.96
#Mann= 3 , 0 , 0
       0      .1       0   476.9    .045       0   491.9      .1       0
Bank Sta=476.9,491.9
XS Rating Curve= 0 ,0
Exp/Cntr=0.3,0.1

Type RM Length L Ch R = 1 ,7452.8  ,292.9,302.2,311.5
XS GIS Cut Line= 3
     1843117.375      174215.414     1843347.823      173822.402
     1843544.722      173403.091
#Sta/Elev= 30
       0 2047.24    24.8 2029.44    74.3 2006.78    89.1 1997.16     104 1989.73
   153.5 1957.02   173.3 1947.83   232.8 1913.69   272.4 1895.88   331.8 1875.19
   376.4  1864.5   450.6  1840.6   465.6 1839.86   476.7 1835.03   480.5 1833.55
   485.5 1833.71   491.7 1836.11   515.4 1850.67   530.3 1864.66   560.2 1888.86
     620 1917.77   644.9 1932.28   664.8 1937.76   679.7    1944   774.4 1994.19
   789.3 2002.91   809.2 2017.81   839.1 2031.84     869  2048.5   918.8 2082.11
#Mann= 3 , 0 , 0
       0      .1       0   476.7    .045       0   491.7      .1       0
Bank Sta=476.7,491.7
XS Rating Curve= 0 ,0
Exp/Cntr=0.3,0.1

Type RM Length L Ch R = 1 ,7150.6  ,275.4,270.2,264.9
XS GIS Cut Line= 3
     1843205.905      174340.913      1843613.72      173964.935
     1843887.918      173728.232
#Sta/Elev= 30
       0 2038.14      30 2020.61      70 2002.75    99.9  1983.4   114.9 1975.48
   134.9 1960.29   179.9 1929.81   199.9 1918.44   214.9 1907.68   234.9 1897.48
   319.8 1840.14   329.8 1836.88   339.8 1835.76   404.8 1830.52   434.8 1830.06
   447.8  1827.7   459.7 1826.03   462.8 1827.43   469.7 1832.01   479.7 1840.93
   509.7 1871.29   529.7 1886.17   589.4 1917.31   629.1 1943.04   658.9 1958.01
   802.8 2043.38   857.4 2071.22   882.2  2085.1     902 2097.36   916.9 2108.88
#Mann= 3 , 0 , 0
       0      .1       0   447.8    .045       0   462.8      .1       0
Bank Sta=447.8,462.8
XS Rating Curve= 0 ,0
Exp/Cntr=0.3,0.1

Type RM Length L Ch R = 1 ,6880.4  ,462,464.3,466.5
XS GIS Cut Line= 3
     1843460.139      174572.803     1843766.917      174110.678
     1843977.006      173815.592
#Sta/Elev= 30
       0 2022.52      20 2012.91      35 2009.31      45  2004.4   154.9 1938.38
   234.9 1893.59   249.9 1886.97   269.8 1874.25   294.8 1862.62   314.8 1854.21
   354.8 1842.17   399.8 1832.59   429.8 1823.32   446.7 1820.61   461.7 1818.19
   464.7 1818.09   474.7 1820.54   489.7 1827.47   519.7 1849.64   539.7 1861.54
   564.6 1886.64   599.3 1904.51   629.1 1922.11   668.8 1956.27   693.6 1967.79
   713.5 1984.42   728.4 1994.46     773 2019.94   812.7    2036   916.9  2102.9
#Mann= 3 , 0 , 0
       0      .1       0   446.7    .045       0   461.7      .1       0
Bank Sta=446.7,461.7
XS Rating Curve= 0 ,0
Exp/Cntr=0.3,0.1

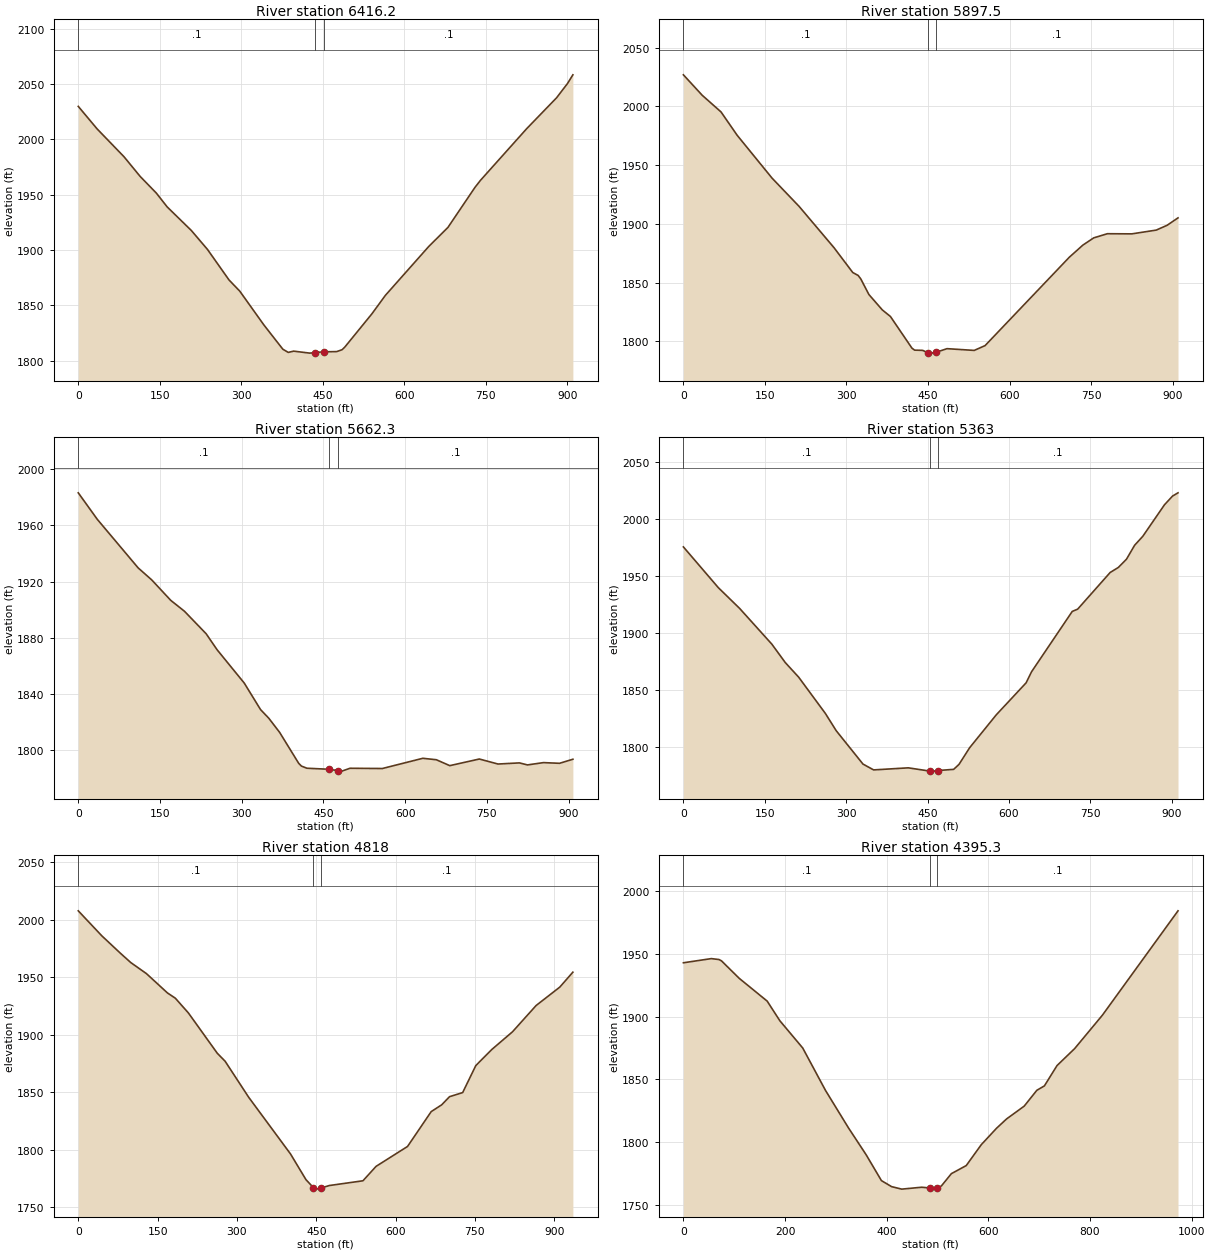
Type RM Length L Ch R = 1 ,6416.2  ,517.6,518.7,519.5
XS GIS Cut Line= 3
     1843760.317      174820.856     1844104.386      174424.156
     1844366.099      174141.792
#Sta/Elev= 30
       0 2029.71    34.7 2009.36    84.2 1984.22   113.9 1966.46   143.7  1951.4
   163.5    1939   208.1 1917.64   237.8 1900.54   277.4 1873.01   297.2 1862.89
   341.8 1832.23   376.5 1810.45   386.4 1807.63   396.3 1808.75     426 1806.96
   436.5 1807.48   451.5 1808.14   475.6 1808.34   485.5 1810.06   490.4  1812.4
   540.1 1842.32   565.1 1859.11   645.1 1903.35   680.1 1920.38   730.1  1956.7
   740.1 1962.96   825.1 2009.58   880.1 2037.47   900.1 2050.29   910.1 2058.19
#Mann= 3 , 0 , 0
       0      .1       0   436.5    .045       0   451.5      .1       0
Bank Sta=436.5,451.5
XS Rating Curve= 0 ,0
Exp/Cntr=0.3,0.1

Type RM Length L Ch R = 1 ,5897.5  ,233,235.2,237.4
XS GIS Cut Line= 3
     1844098.625      175168.107     1844410.273      174836.523
     1844717.287      174500.728
#Sta/Elev= 30
       0 2026.75    34.6 2009.35    69.2 1995.18    98.9 1975.32   163.2 1938.78
   212.7 1914.87     277 1879.69   311.6  1858.5   321.5 1856.02   326.4 1853.02
   341.3 1839.76     366 1826.67   380.9 1821.08   420.4 1794.18   425.4 1792.44
   440.2 1792.25   449.4 1790.32     455  1789.9   464.4 1790.52     485  1793.7
     535 1792.21     555 1796.29     710 1871.51     735 1881.85     755 1888.01
     780 1891.52     825  1891.4     870 1894.61     890 1898.72     910 1905.01
#Mann= 3 , 0 , 0
       0      .1       0   449.4    .045       0   464.4      .1       0
Bank Sta=449.4,464.4
XS Rating Curve= 0 ,0
Exp/Cntr=0.3,0.1

Type RM Length L Ch R = 1 ,5662.3  ,288.8,299.3,310
XS GIS Cut Line= 4
     1844164.934      175247.691     1844516.797      175028.576
     1844731.113      174830.253     1844828.675      174654.322
#Sta/Elev= 30
       0 1983.28      35 1964.34   109.9 1929.74   134.8 1921.18   169.8 1906.57
   194.8 1898.85   234.7 1882.76   254.7  1871.4   304.6  1847.6   334.6 1828.64
   349.6 1822.55   369.6  1812.4   404.5 1790.38   409.5 1788.41   419.5 1786.87
     461 1786.11     476 1785.18   483.8  1784.8   498.6 1786.84     558 1786.66
   632.3 1793.95     657 1792.93   681.8 1788.71     736 1793.43   770.3 1789.86
   809.6 1790.67   824.3 1789.22   853.7 1790.87   883.2 1790.38   907.7 1793.27
#Mann= 3 , 0 , 0
       0      .1       0     461    .045       0     476      .1       0
Bank Sta=461,476
XS Rating Curve= 0 ,0
Exp/Cntr=0.3,0.1

Type RM Length L Ch R = 1 ,5363    ,540.6,545,548.6
XS GIS Cut Line= 4
     1844258.323      175378.875     1844562.608      175276.494
     1844810.512      175196.525     1845109.996      175058.248
#Sta/Elev= 30
       0 1975.76    64.2 1940.05   103.7  1921.7     163 1890.32   187.7 1874.19
   212.4 1861.34   261.8 1829.35   281.5 1814.36   330.9 1785.01   350.5 1779.88
   414.4  1781.7   454.3 1778.82   458.7 1778.81   469.3 1779.34     498 1780.37
   507.8 1784.71   527.5 1799.42   576.6 1828.31   631.5 1856.38   641.5 1866.09
   716.5  1919.1   726.5  1921.1   786.4 1953.32   801.4 1957.71   816.4 1964.95
   831.4  1977.2   846.4 1985.03   886.4 2012.75   901.4 2020.47   911.4 2023.28
#Mann= 3 , 0 , 0
       0      .1       0   454.3    .045       0   469.3      .1       0
Bank Sta=454.3,469.3
XS Rating Curve= 0 ,0
Exp/Cntr=0.3,0.1

Type RM Length L Ch R = 1 ,4818    ,419.5,422.6,425.7
XS GIS Cut Line= 4
     1844256.492      175693.102     1844630.581      175738.843
     1844779.323      175710.055     1845185.973      175699.309
#Sta/Elev= 30
       0 2007.65    44.6 1985.88    79.3 1970.95    99.2 1962.71   128.9 1953.06
   168.6 1936.28   183.5  1931.7   208.3 1918.84   262.8 1883.86   277.7 1876.87
   322.3 1845.53   401.3  1796.3   430.6 1773.91   444.7 1766.99   450.2 1765.72
   459.7 1766.76   474.6 1768.84   538.3 1772.98   563.1 1785.52   622.6 1802.82
   667.3  1833.1   687.1    1839     702 1846.09   726.8 1849.64   751.6 1873.09
   781.4  1886.9   821.1 1902.53   865.7 1925.35   910.4 1941.32   935.2 1954.31
#Mann= 3 , 0 , 0
       0      .1       0   444.7    .045       0   459.7      .1       0
Bank Sta=444.7,459.7
XS Rating Curve= 0 ,0
Exp/Cntr=0.3,0.1

Type RM Length L Ch R = 1 ,4395.3  ,551.2,577.7,604.3
XS GIS Cut Line= 4
       1844321.4      176102.385      1844760.13      176129.091
     1844876.885      176122.694     1845239.837      176327.461
#Sta/Elev= 30
       0 1943.04    54.9 1946.36    69.9 1945.64    74.9 1944.59   109.9 1930.59
   164.8 1912.44   189.8 1896.74   234.8 1874.97   279.7 1841.04   324.7 1811.26
   359.6 1789.72   389.6 1769.11   409.6 1764.29   429.6  1762.3   468.8 1763.81
   484.7 1763.22   499.7 1762.85   507.8 1764.93   527.2 1774.64   556.5 1781.11
   586.2 1797.84     616 1810.85   635.8 1818.32   670.6 1828.59   695.4 1841.21
   710.3 1844.74   735.1 1860.95   769.8 1874.51   824.4 1901.18   973.2 1984.52
#Mann= 3 , 0 , 0
       0      .1       0   484.7    .045       0   499.7      .1       0
Bank Sta=484.7,499.7
XS Rating Curve= 0 ,0
Exp/Cntr=0.3,0.1

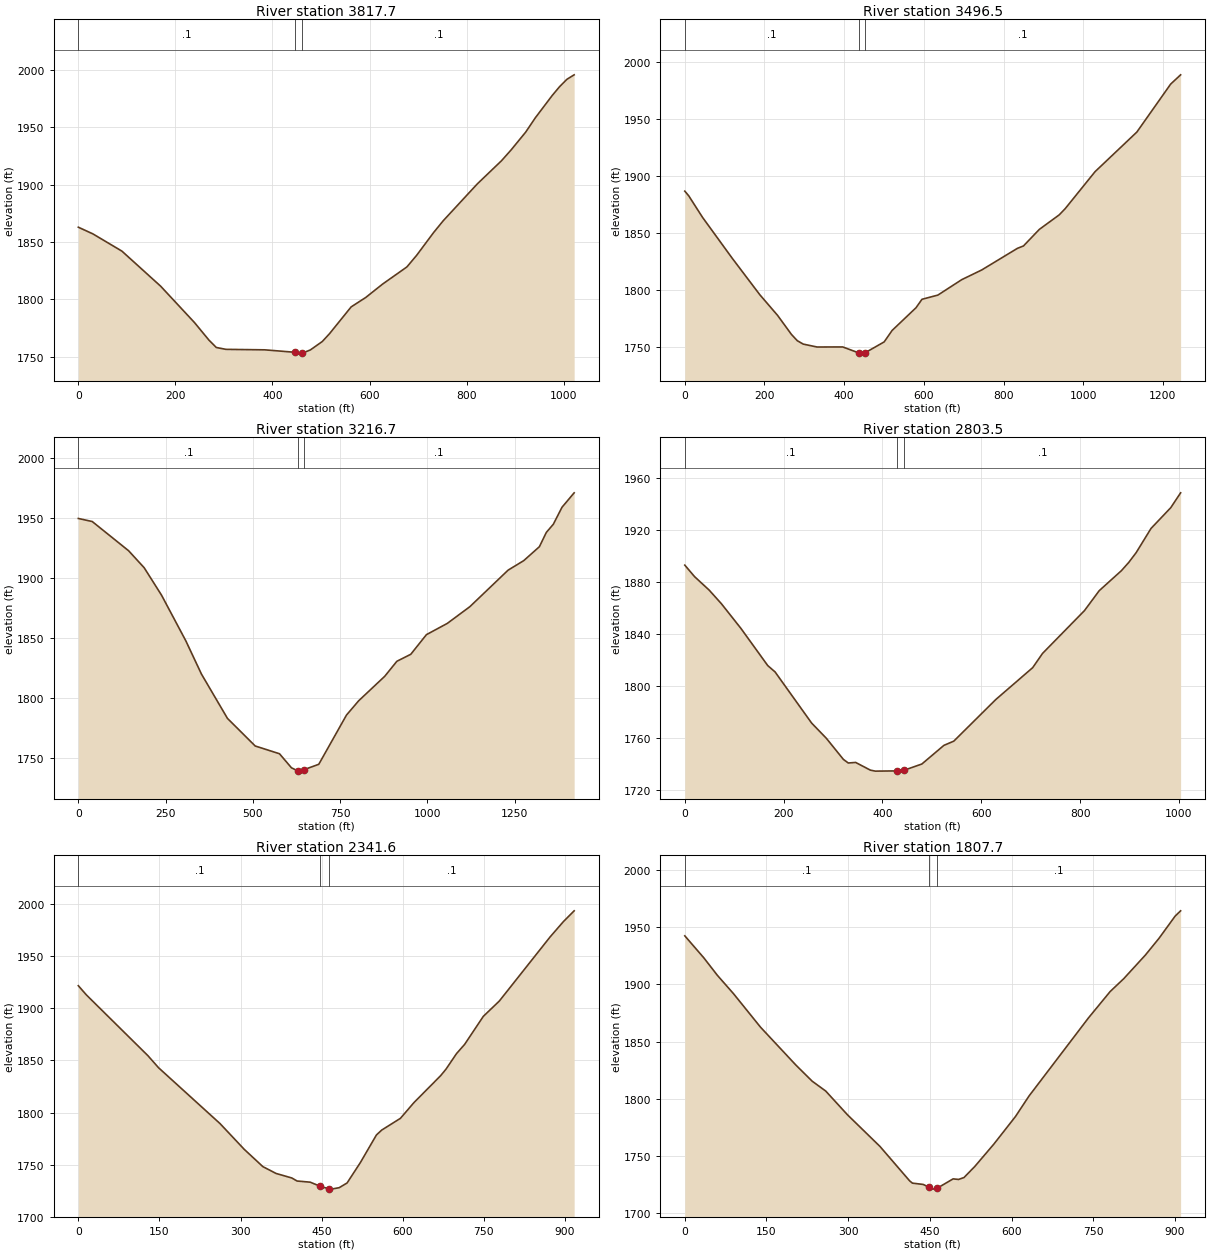
Type RM Length L Ch R = 1 ,3817.7  ,319.5,321.2,322.7
XS GIS Cut Line= 4
      1844250.55       176232.07     1844497.833      176519.339
        1844581.      176682.476     1845040.299      176697.772
#Sta/Elev= 30
       0 1863.03    29.9 1857.22    89.8 1842.17   169.6 1811.59   239.4 1779.84
   269.3 1764.48   284.3 1758.12   304.2 1756.49     384 1756.07   446.6 1753.93
   461.6  1753.2     478 1755.95   502.8 1763.36   517.6 1770.16   562.2 1793.53
   592.1 1801.69   627.1 1813.46     677 1828.36     697 1838.43     732 1858.32
     752  1868.7   821.9  1900.7   871.8 1920.92   891.8 1930.43   921.8 1945.94
   941.8 1958.51   976.8 1978.08   991.7  1985.6  1006.7 1992.01  1021.7 1995.93
#Mann= 3 , 0 , 0
       0      .1       0   446.6    .045       0   461.6      .1       0
Bank Sta=446.6,461.6
XS Rating Curve= 0 ,0
Exp/Cntr=0.3,0.1

Type RM Length L Ch R = 1 ,3496.5  ,327.1,279.8,232.4
XS GIS Cut Line= 4
     1843922.057      176444.169     1844233.935      176688.873
      1844273.92      176784.836     1845016.031      176730.457
#Sta/Elev= 30
       0 1886.71     9.9 1882.62    44.6 1863.72   118.9 1828.01   188.3 1795.99
   232.9  1777.9   267.6 1761.26   282.4 1755.72   297.3 1752.74     332  1750.2
   396.4 1750.26   436.1 1745.11   445.9 1744.84   451.1 1744.86   500.4 1754.67
   520.4 1764.72   580.3 1784.58   595.3 1791.99   635.2 1795.67   695.1 1809.19
   745.1 1817.65     835 1836.65     850  1838.7   889.9 1853.23   939.8 1865.95
   954.8 1871.39  1029.7 1903.77  1134.6 1938.46  1219.5 1980.49  1244.5 1988.61
#Mann= 3 , 0 , 0
       0      .1       0   436.1    .045       0   451.1      .1       0
Bank Sta=436.1,451.1
XS Rating Curve= 0 ,0
Exp/Cntr=0.3,0.1

Type RM Length L Ch R = 1 ,3216.7  ,417.9,413.2,408.5
XS GIS Cut Line= 4
     1843635.768      177120.705     1844192.352       176952.77
      1844273.92      176855.208     1844980.857      176768.814
#Sta/Elev= 30
       0 1949.44    39.8  1946.9   144.1 1922.57   188.8 1908.38   238.5 1885.56
   308.1 1847.55   352.8 1819.93   427.3 1783.05   506.8 1760.08   576.4 1753.62
   610.7 1741.93   630.3 1739.16   630.6 1739.16   645.6 1740.26     689 1744.86
   768.3 1785.79   803.2 1797.69   877.9 1818.07   912.7 1830.57   952.6 1836.41
   997.4 1852.74  1057.2  1862.1  1121.9 1876.03  1231.5 1906.44  1276.3 1914.35
  1321.1 1925.94    1341 1937.84    1361 1944.62  1385.9 1958.78  1420.7 1970.78
#Mann= 3 , 0 , 0
       0      .1       0   630.6    .045       0   645.6      .1       0
Bank Sta=630.6,645.6
XS Rating Curve= 0 ,0
Exp/Cntr=0.3,0.1

Type RM Length L Ch R = 1 ,2803.5  ,455,461.9,468.9
XS GIS Cut Line= 4
     1844386.844      177514.487     1844512.227      177240.658
     1844617.786      177043.935     1845053.869      176845.625
#Sta/Elev= 30
       0 1892.89    19.8 1884.01    49.4 1873.62    74.1 1863.15   113.6 1844.15
   167.9 1815.51   182.7 1810.64   256.7 1771.24   286.4 1759.56     321 1743.25
   330.9 1740.49   345.8 1740.92   375.6 1734.99   385.5 1734.23   428.7  1734.4
   443.7  1734.9   479.8 1739.71   524.4 1754.07   544.4 1757.31   629.2  1789.3
   704.1 1813.92     724 1824.87   808.9 1857.86   838.8 1873.22   883.7 1888.63
   898.7 1895.05   913.7 1902.61   943.6 1921.14   983.5 1937.11  1003.5 1948.57
#Mann= 3 , 0 , 0
       0      .1       0   428.7    .045       0   443.7      .1       0
Bank Sta=428.7,443.7
XS Rating Curve= 0 ,0
Exp/Cntr=0.3,0.1

Type RM Length L Ch R = 1 ,2341.6  ,530.8,534,537.1
XS GIS Cut Line= 4
     1844663.518      177734.363      1844864.09      177458.173
     1844979.245      177346.217     1845244.513      177026.863
#Sta/Elev= 30
       0 1921.58    14.8 1912.81   128.6 1854.59   148.4 1842.97   262.2 1789.41
   306.7 1764.87   341.3 1748.22   365.7 1741.69   394.9 1737.34   404.6 1734.43
   428.9 1733.32   447.9 1729.27   462.9 1727.05   467.9 1726.66   482.5 1728.04
   497.1 1732.57   521.7 1752.13   551.4 1778.58   561.2 1783.26   595.8 1794.51
   620.6 1809.48     670 1835.29   679.9 1841.49   699.6 1856.57   714.5 1865.33
   749.1 1892.21   778.7 1906.89   872.6 1968.31   897.3 1983.05   917.1 1993.33
#Mann= 3 , 0 , 0
       0      .1       0   447.9    .045       0   462.9      .1       0
Bank Sta=447.9,462.9
XS Rating Curve= 0 ,0
Exp/Cntr=0.3,0.1

Type RM Length L Ch R = 1 ,1807.7  ,489,490.1,491.1
XS GIS Cut Line= 3
     1844896.204      178064.201     1845353.499      177728.468
     1845620.792      177513.398
#Sta/Elev= 30
       0 1942.44    34.8 1923.31    59.7 1908.04    89.6 1891.84   139.3 1862.54
     204  1829.6   233.9 1815.52   258.8  1806.9   298.6 1786.23   358.3 1758.59
     413 1728.41     418 1726.51   437.9 1725.36   447.6 1723.04   457.8 1721.28
   462.6 1721.86   492.7 1730.23   502.6 1729.73   512.6 1731.39   532.5 1741.07
   567.3 1760.49   607.1 1784.63   631.9 1802.49   741.3 1870.85   781.1 1893.84
     806 1905.05   845.7 1925.66   870.6  1940.2   900.4 1959.71   910.4 1964.28
#Mann= 3 , 0 , 0
       0      .1       0   447.6    .045       0   462.6      .1       0
Bank Sta=447.6,462.6
XS Rating Curve= 0 ,0
Exp/Cntr=0.3,0.1

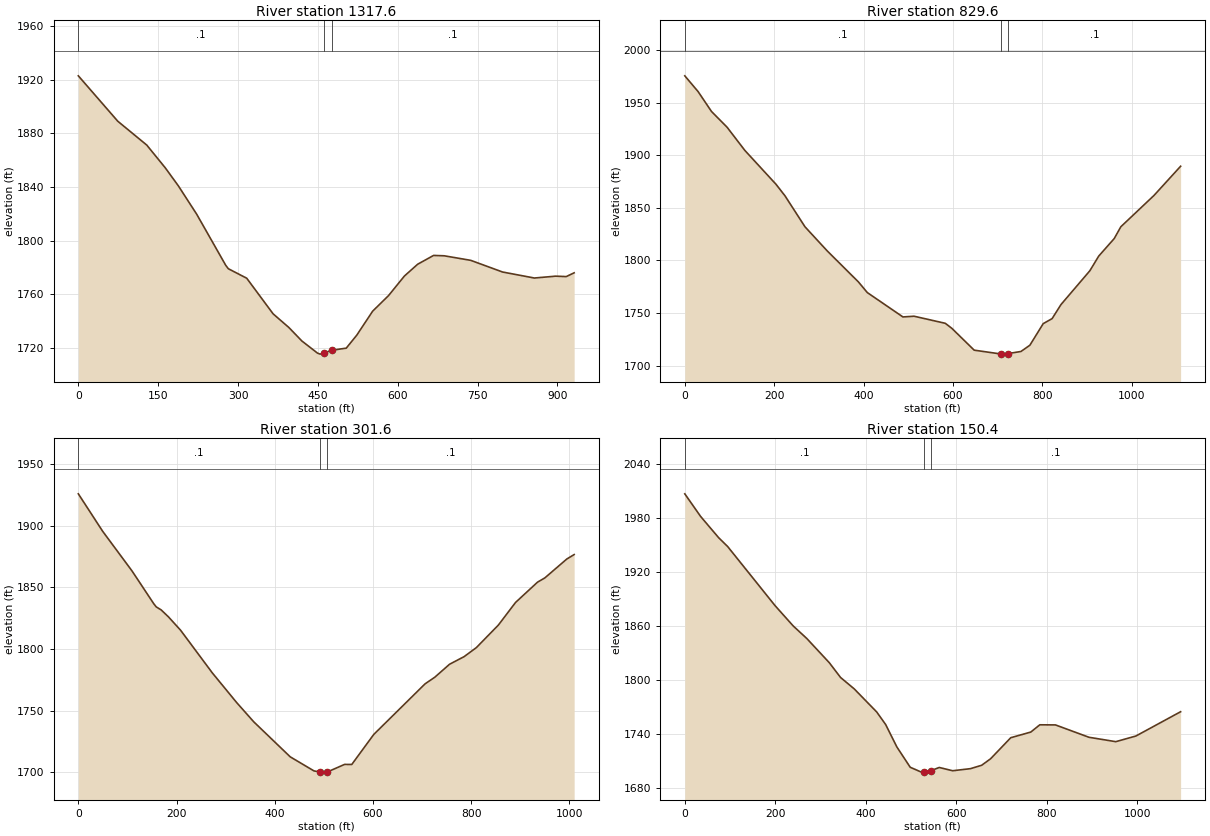
Type RM Length L Ch R = 1 ,1317.6  ,500.6,488,473.3
XS GIS Cut Line= 4
     1845181.124      178479.329     1845491.046      178225.874
     1845588.607        178160.3       1845832.9      177826.831
#Sta/Elev= 30
       0 1923.02    74.1 1889.14   128.5 1871.36   163.1 1854.47   187.8 1840.96
   222.4  1819.7   276.8 1781.67   281.7 1779.08   316.3 1771.98   365.8 1745.43
   395.4 1735.23     420  1725.1   449.3 1716.08   454.2 1715.34   460.6 1716.01
   475.6 1718.21   503.2  1719.8   522.9 1729.43   552.8 1747.38   582.7 1759.03
   612.5 1773.63   637.4 1782.43   667.3 1788.99   687.2 1788.72     737 1785.33
   796.8 1776.62   856.6 1772.13   896.4 1773.52   916.4  1773.2   931.3 1776.02
#Mann= 3 , 0 , 0
       0      .1       0   460.6    .045       0   475.6      .1       0
Bank Sta=460.6,475.6
XS Rating Curve= 0 ,0
Exp/Cntr=0.3,0.1

Type RM Length L Ch R = 1 ,829.6   ,502.3,528,556.3
XS GIS Cut Line= 4
     1845475.665      178731.025     1845884.492      178464.181
     1846001.247       178109.12     1846238.235       178036.93
#Sta/Elev= 30
       0  1975.4    29.9 1960.35    59.8 1941.51    94.6 1926.59   134.5 1904.49
   204.2 1872.32   224.2 1861.41     269 1831.96   318.8 1809.04   388.6 1779.58
   408.5 1769.46   488.2 1746.31   513.1    1747   582.9 1740.28   597.8 1735.44
   647.7 1714.74   708.1 1711.07   712.5 1710.98   723.1 1711.49   752.3 1713.49
   772.3 1719.43   802.2 1739.96   822.1 1744.72     842  1758.1   906.6 1790.22
   926.4 1804.12   961.1 1820.78   975.9 1831.99  1050.2 1861.79  1109.7  1889.5
#Mann= 3 , 0 , 0
       0      .1       0   708.1    .045       0   723.1      .1       0
Bank Sta=708.1,723.1
XS Rating Curve= 0 ,0
Exp/Cntr=0.3,0.1

Type RM Length L Ch R = 1 ,301.6   ,161.6,151.2,140.8
XS GIS Cut Line= 4
     1845537.427      178860.827     1845929.275      178657.706
     1846039.632      178656.107     1846409.088      178385.812
#Sta/Elev= 30
       0 1925.75    49.6 1895.37   109.1 1863.39   153.7 1836.64   158.7 1834.13
   168.6 1831.71   183.5 1826.06   208.3 1815.18   272.8 1780.67   322.3 1756.65
   357.1 1741.04   431.4 1712.66   479.8 1701.24   491.5 1700.44   503.8 1700.26
   506.5 1700.31   542.1 1706.53   556.7 1706.44   601.5 1730.79     706  1771.8
   725.9  1777.2   755.7 1787.63   785.6 1793.87   810.5 1801.19   855.3 1819.45
   890.1 1837.71   934.9 1854.16   949.8 1857.62   994.6 1872.95  1009.5 1876.53
#Mann= 3 , 0 , 0
       0      .1       0   491.5    .045       0   506.5      .1       0
Bank Sta=491.5,506.5
XS Rating Curve= 0 ,0
Exp/Cntr=0.3,0.1

Type RM Length L Ch R = 1 ,150.4   ,177.1,150.4,123.4
XS GIS Cut Line= 4
     1845529.832       179096.47     1845889.168      178852.829
     1846131.448      178730.328     1846471.827      178539.253
#Sta/Elev= 30
       0 2006.91    34.9 1981.81    74.8 1958.16    94.8 1948.27   199.6 1882.56
   239.5 1860.09   269.5 1846.16   319.4 1819.18   344.3 1802.73   374.3 1790.15
   424.2  1764.4     444 1750.42   468.7 1725.56   498.3  1702.9     523  1697.5
   528.6  1697.8   543.6 1699.06   562.5 1702.67   592.1 1699.03   631.6 1701.37
   656.3 1705.14     676 1712.37   720.5 1735.74   764.9 1742.07   784.7 1750.11
   819.3 1749.99   893.4 1736.25   952.7 1731.36   997.2 1737.66    1096 1764.65
#Mann= 3 , 0 , 0
       0      .1       0   528.6    .045       0   543.6      .1       0
Bank Sta=528.6,543.6
XS Rating Curve= 0 ,0
Exp/Cntr=0.3,0.1

Chan Stop Cuts=-1
Use User Specified Reach Order=0